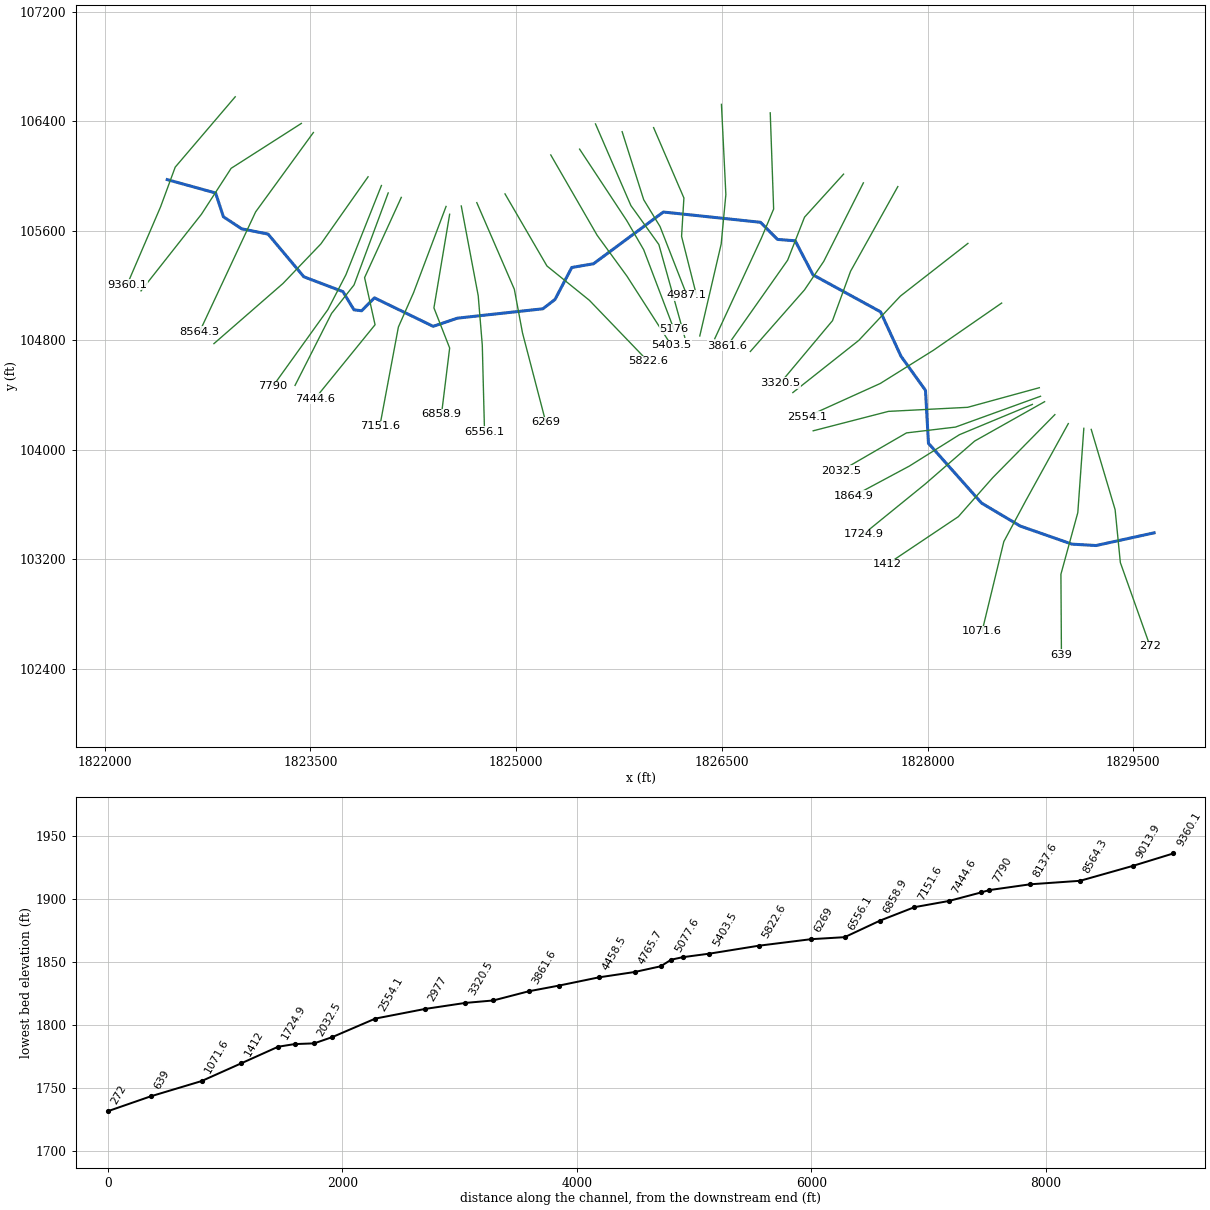
--- Laurel Branch A.prj (project) ---

Proj Title=LaurelBrA
Current Plan=p01
Default Exp/Contr=0,0
English Units
Geom File=g01
Flow File=f01
Plan File=p01
BEGIN DESCRIPTION:
END DESCRIPTION:
DSS Export Rating Curves= 0
DSS Export Rating Curve Sorted= 0
DSS Export Volume Flow Curves= 0
DXF OffsetX= 0
DXF OffsetY= 0
DXF ScaleX= 0
DXF ScaleY= 0

--- Laurel Branch A.p01 (plan) ---

Plan Title=Floodplain
Program Version=4.00
Geom File=g01
Flow File=f01
K Sum by GR=0
Std Step Tol=0.01
Critical Tol=0.01
Num of Std Step Trials=20
Max Error Tol=0.3
Flow Tol Ratio=0.001
Split Flow NTrial=30
Split Flow Tol=0.02
Split Flow Ratio=0.02
Log Output Level=0
Friction Slope Method=1
Unsteady Friction Slope Method=2
Unsteady Bridges Friction Slope Method=1
Global Log Level=0
CheckData=False
Run HTab=0
Run UNet=0
Run PostProcess=0
UNET Theta=0
UNET Theta Warmup=0
UNET ZTol=0
UNET ZSATol=0
UNET MxIter=0
UNET MaxInSteps=0
UNET DtIC=0
UNET DtMin=0
UNET MaxCRTS=0
UNET WFStab=0
UNET SFStab=0
UNET WFX=0
UNET SFX=0
UNET DSS MLevel=0
UNET DZMax Abort=0
UNET Convert EG Bridges=0
UNET Use Existing IB Tables=0
UNET Froude Limit=0
UNET Froude Power=0
Write IC File=0
Echo Input=False
Echo Output=False
Write Detailed=0

--- Laurel Branch A.f01 (steady flow) ---

Flow Title=NFF Regression Equation
Program Version=4.00
Number of Profiles=1
Profile Names=P100yr
River Rch & RM=Laurel Branch A,Main      ,9360.1
650.5030
River Rch & RM=Laurel Branch A,Main      ,7718
677.6742
River Rch & RM=Laurel Branch A,Main      ,7151.6
752.4712
River Rch & RM=Laurel Branch A,Main      ,4765.7
827.7684
River Rch & RM=Laurel Branch A,Main      ,4458.5
923.4025
River Rch & RM=Laurel Branch A,Main      ,3560.7
959.2003
River Rch & RM=Laurel Branch A,Main      ,272
1050.835
Boundary for River Rch & Prof#=Laurel Branch A,Main      ,1
Up Type=0
Dn Type=3
Dn Slope=0.03407

--- Laurel Branch A.g01 (geometry) ---

Geom Title=USGS 10m DEM
Program Version=4.00

River Reach=LaurelBrA       ,Main
Reach XY= 30
     1822455.165      105972.956     1822808.052      105875.179
     1822864.774      105701.676     1822997.126      105613.813
     1823190.648      105574.886     1823451.458      105262.914
     1823736.737      105154.475     1823816.815      105021.567
     1823872.981      105014.338     1823966.406      105108.875
     1824394.953      104900.715     1824571.441      104960.396
     1825195.029      105029.064     1825283.248      105097.197
     1825405.589      105330.758     1825564.077      105358.007
     1826073.464      105736.154     1826781.934      105661.081
     1826905.944      105535.959     1827034.959      105525.949
     1827165.086      105276.817     1827657.233      105007.109
     1827806.268      104682.903     1827985.331      104432.659
     1828007.019      104045.614     1828394.064      103609.076
     1828676.006      103441.135     1829054.154      103308.783
     1829229.325      103298.774     1829652.384      103391.444

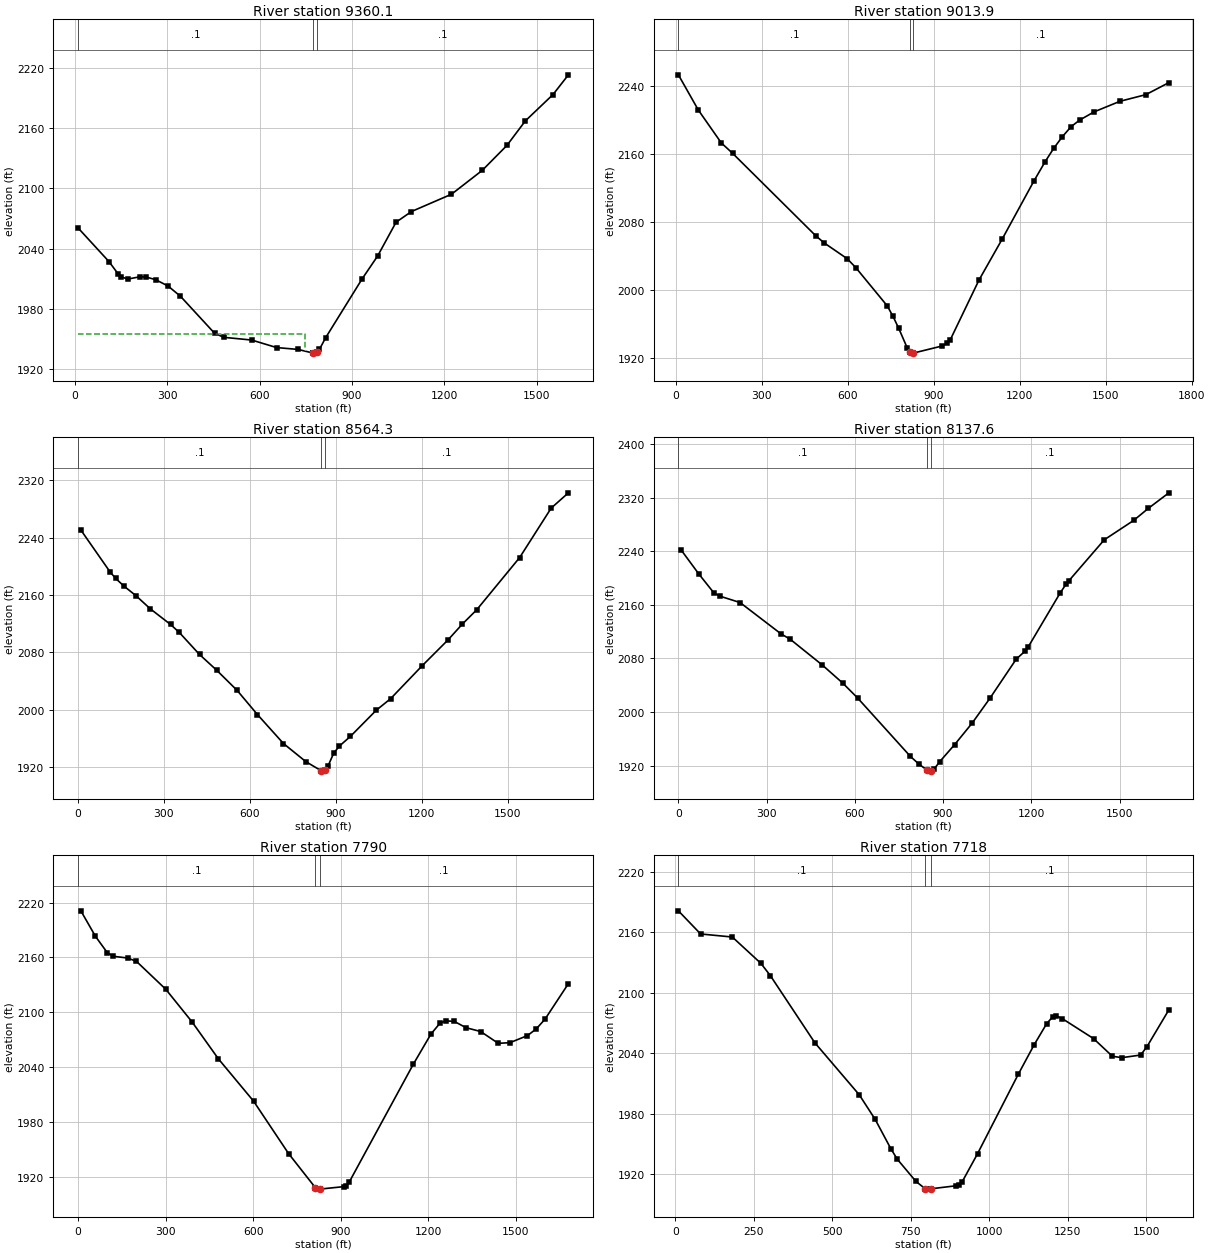
Type RM Length L Ch R = 1 ,9360.1  ,351.2,346.2,342
XS GIS Cut Line= 4
     1822951.061      106578.253     1822513.332      106064.028
     1822407.087      105775.041     1822162.821      105205.597
#Sta/Elev= 30
    10.1 2060.76   110.9 2027.16   141.1 2014.72   151.2 2012.03   171.3 2009.77
   211.7 2012.08   231.8 2011.78   262.1 2009.24   302.4 2002.94   342.7 1992.81
   453.6    1956   483.8 1951.89   574.5 1949.19   655.1 1941.72     725 1939.86
     772 1936.37   774.6 1936.19     787 1937.59   794.5 1940.06   814.4 1951.47
   933.5 2010.26   983.2 2032.69  1043.2 2066.33  1093.1 2076.92  1223.1 2094.12
    1323 2117.83  1402.9 2142.56  1462.9 2166.99  1552.9 2193.24  1602.8  2212.8
#Mann= 3 , 0 , 0
    10.1      .1       0     772    .045       0     787      .1       0
#XS Ineff= 2 , 0
          747.14 1955.33
Permanent Ineff=
       F       F
Bank Sta=772,787
XS Rating Curve= 0 ,0
Exp/Cntr=0.3,0.1

Type RM Length L Ch R = 1 ,9013.9  ,437,449.6,461.3
XS GIS Cut Line= 4
     1823433.606      106383.898     1822921.312      106055.528
     1822704.573      105719.794     1822263.995      105159.963
#Sta/Elev= 30
      10  2253.4    79.8 2211.86   159.6 2173.39   199.5 2161.01   488.8  2064.3
   518.7 2055.76   598.5 2037.31   628.5 2026.88   738.4 1981.81   758.4 1969.52
   778.3 1955.51   808.3 1932.22   818.3 1927.23   828.3 1926.29   829.2 1926.33
   928.2 1934.55   948.2 1937.88   958.2 1941.98  1058.3 2012.19  1138.6 2059.97
  1248.9 2128.02  1289.1  2151.4  1319.2 2167.17  1349.3 2180.76  1379.4 2192.45
  1409.5 2200.23  1459.6 2209.84  1549.9 2222.29  1640.2 2230.11  1720.5 2244.23
#Mann= 3 , 0 , 0
      10      .1       0   818.3    .045       0   829.2      .1       0
Bank Sta=818.3,829.2
XS Rating Curve= 0 ,0
Exp/Cntr=0.3,0.1

Type RM Length L Ch R = 1 ,8564.3  ,444,426.8,409.5
XS GIS Cut Line= 3
     1823521.162      106317.269     1823099.804      105736.793
     1822691.297      104861.299
#Sta/Elev= 30
    10.1 2250.62   111.1 2192.75   131.3 2183.22   161.6 2172.05   202.1 2159.17
   252.6  2140.7   323.3 2118.89   353.6 2107.83   424.3 2077.06   484.9 2054.87
   555.6 2026.99   626.4 1993.35   717.3 1952.94   795.2 1927.77   848.9 1915.03
   853.6 1914.47   863.9 1916.41   873.1 1921.87   892.6 1939.43   912.1 1949.28
     951  1962.9  1041.1 1999.32  1091.2 2015.43  1201.3 2061.33  1291.4 2097.31
  1341.4 2119.36  1391.5 2139.26  1541.6 2212.19  1651.7 2281.15  1711.8 2302.43
#Mann= 3 , 0 , 0
       0      .1       0   848.9    .045       0   863.9      .1       0
Bank Sta=848.9,863.9
XS Rating Curve= 0 ,0
Exp/Cntr=0.3,0.1

Type RM Length L Ch R = 1 ,8137.6  ,341,347.5,354.1
XS GIS Cut Line= 4
     1823919.967      105993.551     1823575.781      105503.054
     1823299.544      105214.068     1822795.794       104774.18
#Sta/Elev= 30
      10 2241.56    69.9 2205.84   119.8 2178.35   139.8 2173.15   209.7 2163.45
   349.5 2116.47   379.5 2108.87   489.4 2070.11   559.3 2042.96   609.2    2021
   789.1 1933.57   819.1 1921.73   844.7 1913.55   859.1 1911.68   859.7 1911.86
   869.1 1914.54     889 1926.03     939 1951.09     999 1983.45  1058.9 2020.19
  1148.7  2078.9  1178.7 2090.86  1188.6 2096.48  1298.4 2177.94  1318.4 2191.01
  1328.4 2196.27  1448.2 2257.18    1548 2286.04  1597.9 2304.06  1667.8 2327.29
#Mann= 3 , 0 , 0
       0      .1       0   844.7    .045       0   859.7      .1       0
Bank Sta=844.7,859.7
XS Rating Curve= 0 ,0
Exp/Cntr=0.3,0.1

Type RM Length L Ch R = 1 ,7790    ,76.3,72.1,67.8
XS GIS Cut Line= 4
     1824017.351      105929.904     1823758.522      105277.815
     1823626.779      105022.827     1823224.571       104461.09
#Sta/Elev= 30
      10 2210.92    60.1    2183   100.2 2165.38   120.3 2161.33   170.4 2159.38
   200.5  2155.7   300.7 2125.31   390.9 2089.59   481.1 2049.26   601.4 2003.14
   721.4 1945.85   812.9 1908.75   820.3  1907.1   827.9 1907.11   909.4 1909.79
   919.3 1910.96   929.2 1914.95  1148.8 2043.68  1208.9 2076.42  1238.9 2087.94
  1258.9 2090.86    1289 2090.16    1329 2083.32  1379.1 2079.15  1439.2 2066.28
  1479.2 2066.97  1539.3 2074.72  1569.3    2082  1599.4 2092.64  1679.5 2131.45
#Mann= 3 , 0 , 0
       0      .1       0   812.9    .045       0   827.9      .1       0
Bank Sta=812.9,827.9
XS Rating Curve= 0 ,0
Exp/Cntr=0.3,0.1

Type RM Length L Ch R = 1 ,7718    ,250.8,273.4,295.6
XS GIS Cut Line= 4
       1824066.8      105875.681     1823817.569        105203.1
     1823653.692      104994.838      1823387.39      104469.063
#Sta/Elev= 30
    10.1 2181.14    80.8  2158.2   181.8 2155.16   272.8 2129.04   303.1 2116.78
   444.5 2050.31   585.9 1998.73   636.5 1974.38     687 1944.95   707.2 1934.77
   766.3 1912.86   795.8  1905.6   805.6 1905.19   815.4 1905.58   893.9  1908.5
   903.8  1909.5   913.6 1912.49   962.7 1940.43  1092.2  2019.1  1142.1 2047.99
  1182.1 2069.02    1202 2076.25    1212 2077.07    1232  2074.3  1331.9 2054.42
  1391.8 2036.92  1421.8 2035.54  1481.7 2038.14  1501.7 2046.38  1571.6 2082.97
#Mann= 3 , 0 , 0
    10.1      .1       0   795.8    .045       0   815.4      .1       0
Bank Sta=795.8,815.4
XS Rating Curve= 0 ,0
Exp/Cntr=0.3,0.1

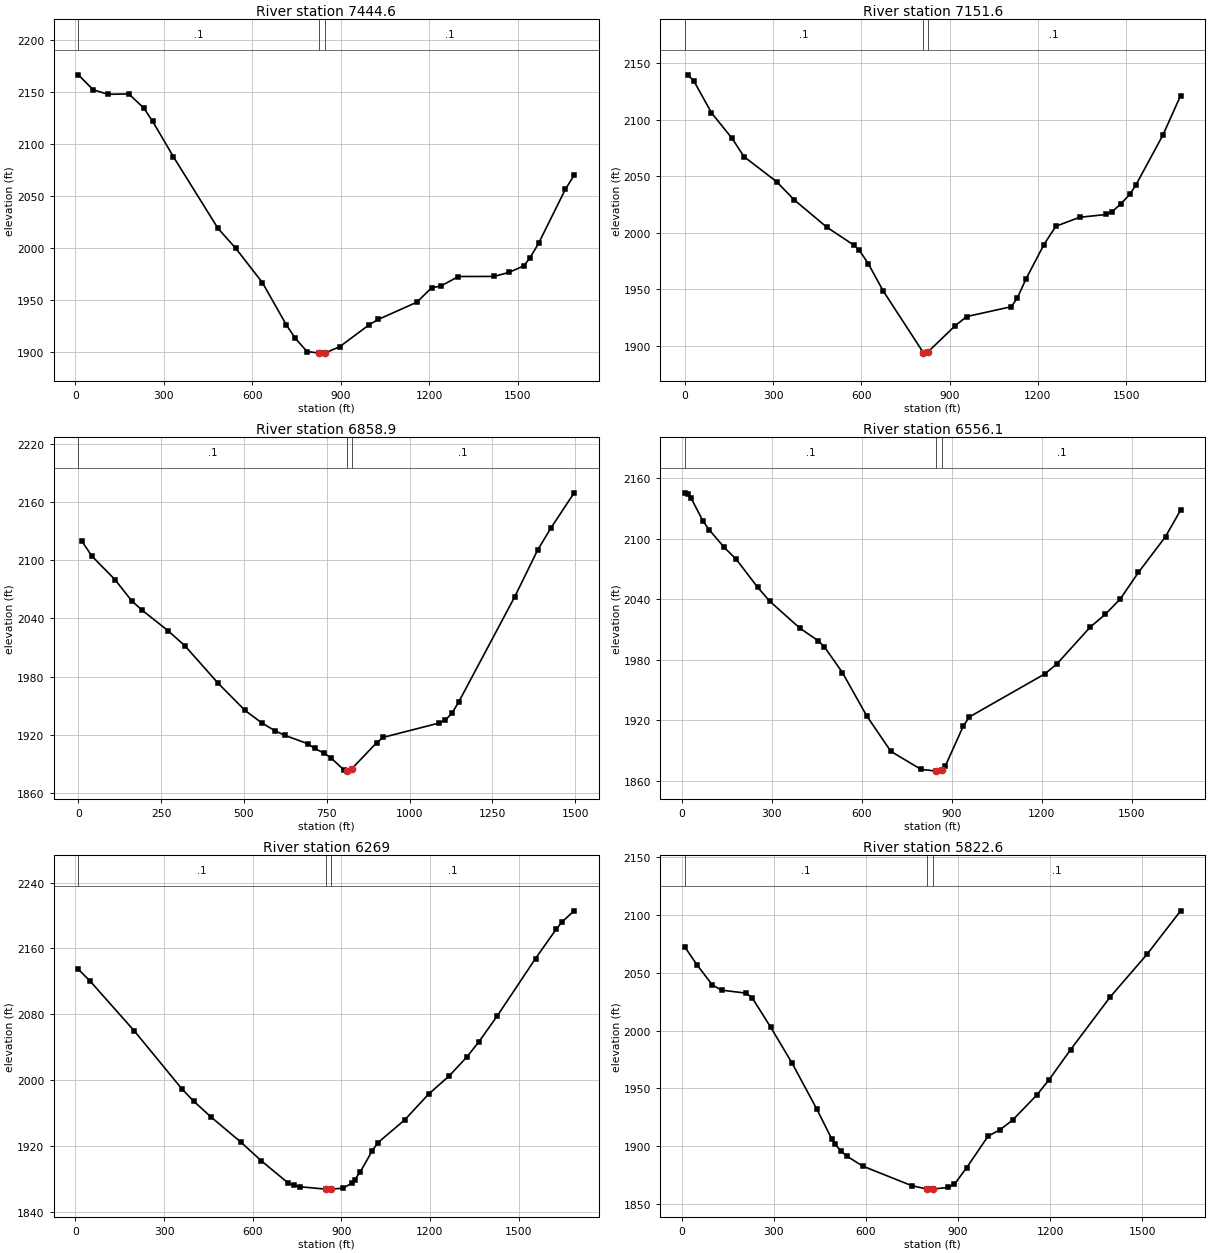
Type RM Length L Ch R = 1 ,7444.6  ,309,293,275.5
XS GIS Cut Line= 4
     1824162.253      105843.038     1823894.516      105256.566
     1823971.012      104912.332     1823533.283      104372.608
#Sta/Elev= 30
    10.1 2166.56    60.4 2152.17   110.8 2147.79   181.3 2148.16   231.7 2134.66
   261.9 2121.91   332.4 2087.75   483.5 2018.77     544 1999.47   634.6 1966.36
   715.2 1925.95   745.4    1913   785.7 1900.01   825.8 1898.54   836.1 1898.45
   846.2  1898.5   896.6 1904.59   997.3 1925.89  1027.5 1930.88  1158.5 1947.51
  1208.8 1961.51    1239  1962.9  1299.5 1972.26  1420.3 1972.34  1470.7  1976.2
    1521 1982.45  1541.2 1989.72  1571.4 2004.17    1662 2056.09  1692.2 2069.85
#Mann= 3 , 0 , 0
    10.1      .1       0   825.8    .045       0   846.2      .1       0
Bank Sta=825.8,846.2
XS Rating Curve= 0 ,0
Exp/Cntr=0.3,0.1

Type RM Length L Ch R = 1 ,7151.6  ,274.6,292.6,310.7
XS GIS Cut Line= 4
     1824488.783      105777.032     1824251.499      105146.071
     1824141.004      104895.333     1824005.628      104170.729
#Sta/Elev= 30
    10.1  2139.6    30.2 2134.43    90.6 2106.03     161 2083.33   201.2 2067.26
   311.9 2045.17   372.3 2028.98   482.9 2004.84   573.5 1989.26   593.6 1984.33
   623.8 1972.58   674.1 1948.65   810.7 1894.01   820.9 1893.56   825.7 1894.43
   918.8 1917.72   958.2 1925.89  1109.7  1934.6  1129.9 1942.16  1160.2 1959.38
  1220.8 1989.55  1261.1 2005.72  1341.9 2013.64  1432.8 2016.13    1453 2018.76
  1483.3 2025.76  1513.6 2034.31  1533.8 2042.49  1624.7 2086.13  1685.3 2121.27
#Mann= 3 , 0 , 0
       0      .1       0   810.7    .045       0   825.7      .1       0
Bank Sta=810.7,825.7
XS Rating Curve= 0 ,0
Exp/Cntr=0.3,0.1

Type RM Length L Ch R = 1 ,6858.9  ,309.4,302.9,296.3
XS GIS Cut Line= 4
     1824514.986      105719.794     1824400.242      105035.576
     1824514.986       104742.34     1824455.489      104257.863
#Sta/Elev= 30
    10.1 2119.92    40.2 2104.41   110.6 2079.97   160.9 2058.24     191 2048.95
   271.5 2027.17   321.7 2011.91   422.3 1973.24   502.7 1945.57     553 1932.75
   593.2 1924.53   623.4 1919.75   693.8 1910.98   713.5 1906.23     743 1901.16
   762.7 1896.58     802 1884.08   809.9 1883.16   811.9 1882.93   824.9 1885.12
   900.4 1912.15   920.1 1917.68  1088.4 1932.33  1108.3 1935.57  1128.2 1942.67
  1148.1 1953.95  1317.5 2062.39  1387.2  2110.8    1427 2133.25  1496.8 2169.26
#Mann= 3 , 0 , 0
       0      .1       0   809.9    .045       0   824.9      .1       0
Bank Sta=809.9,824.9
XS Rating Curve= 0 ,0
Exp/Cntr=0.3,0.1

Type RM Length L Ch R = 1 ,6556.1  ,284.8,287.1,289.4
XS GIS Cut Line= 4
     1824599.735      105780.282     1824723.227      105124.822
     1824752.975      104763.589     1824769.289      104129.793
#Sta/Elev= 30
    10.1 2145.34    20.2 2143.82    30.3 2140.55    70.7 2117.46      91 2108.88
   141.5 2091.32   181.9 2079.44   252.6 2051.96   293.1 2038.08   394.1 2011.24
   454.8  1998.9     475 1993.08   535.6 1967.41   616.5 1924.57   697.2 1889.33
   797.9 1871.48   848.2 1869.85   858.3 1869.76   868.4 1870.41   878.4 1874.55
   938.8 1914.34     959 1923.43  1210.6 1966.01  1250.8 1975.87  1361.5 2012.25
  1411.9 2024.92  1462.2 2040.21  1522.6 2066.45  1613.1 2101.95  1663.5 2128.31
#Mann= 3 , 0 , 0
    10.1      .1       0   848.2    .045       0   868.4      .1       0
Bank Sta=848.2,868.4
XS Rating Curve= 0 ,0
Exp/Cntr=0.3,0.1

Type RM Length L Ch R = 1 ,6269    ,431.1,446.4,462.3
XS GIS Cut Line= 4
     1824712.936        105804.8     1824986.714       105171.57
     1825046.211      104852.835     1825216.099      104200.528
#Sta/Elev= 30
      10 2134.81      50 2120.36     200 2059.79   359.9 1989.99   399.9 1974.95
   459.9 1955.38   559.9 1925.26   629.9 1902.31   719.4  1875.8     739 1872.62
   758.7 1871.07   847.1 1868.17   856.9 1868.16   866.7 1868.26     906 1869.28
   935.5 1875.44   945.3 1879.28     965 1889.52  1004.3 1914.39  1024.2 1924.63
  1114.7 1952.13  1195.2  1983.3  1265.6 2005.54    1326 2028.85  1366.2 2047.11
  1426.6 2077.53  1557.4 2147.85  1627.8 2183.56  1647.9 2192.52  1688.2 2205.68
#Mann= 3 , 0 , 0
      10      .1       0   847.1    .045       0   866.7      .1       0
Bank Sta=847.1,866.7
XS Rating Curve= 0 ,0
Exp/Cntr=0.3,0.1

Type RM Length L Ch R = 1 ,5822.6  ,424.6,419.1,412.9
XS GIS Cut Line= 4
     1824918.717      105868.537     1825224.703      105341.562
     1825534.542      105090.444     1825962.059      104644.913
#Sta/Elev= 30
      10 2072.24    49.9 2056.68    99.9 2039.34   129.9 2034.87   209.8 2032.31
   229.8  2028.2   289.7 2002.92   359.6 1971.83   439.5 1932.43   489.5 1906.02
   499.5 1901.87   519.5  1895.7   539.4 1891.25   589.4  1882.9     749 1866.01
   798.8 1863.09   808.8 1862.97   818.8 1863.03   868.6 1864.48   888.5 1867.15
   928.4 1881.46   998.2 1908.71  1038.1 1914.44  1077.9 1922.54  1157.6 1944.45
  1197.4 1957.62  1267.1 1983.46  1396.6 2029.14  1516.1 2065.83  1625.7 2103.42
#Mann= 3 , 0 , 0
      10      .1       0   798.8    .045       0   818.8      .1       0
Bank Sta=798.8,818.8
XS Rating Curve= 0 ,0
Exp/Cntr=0.3,0.1

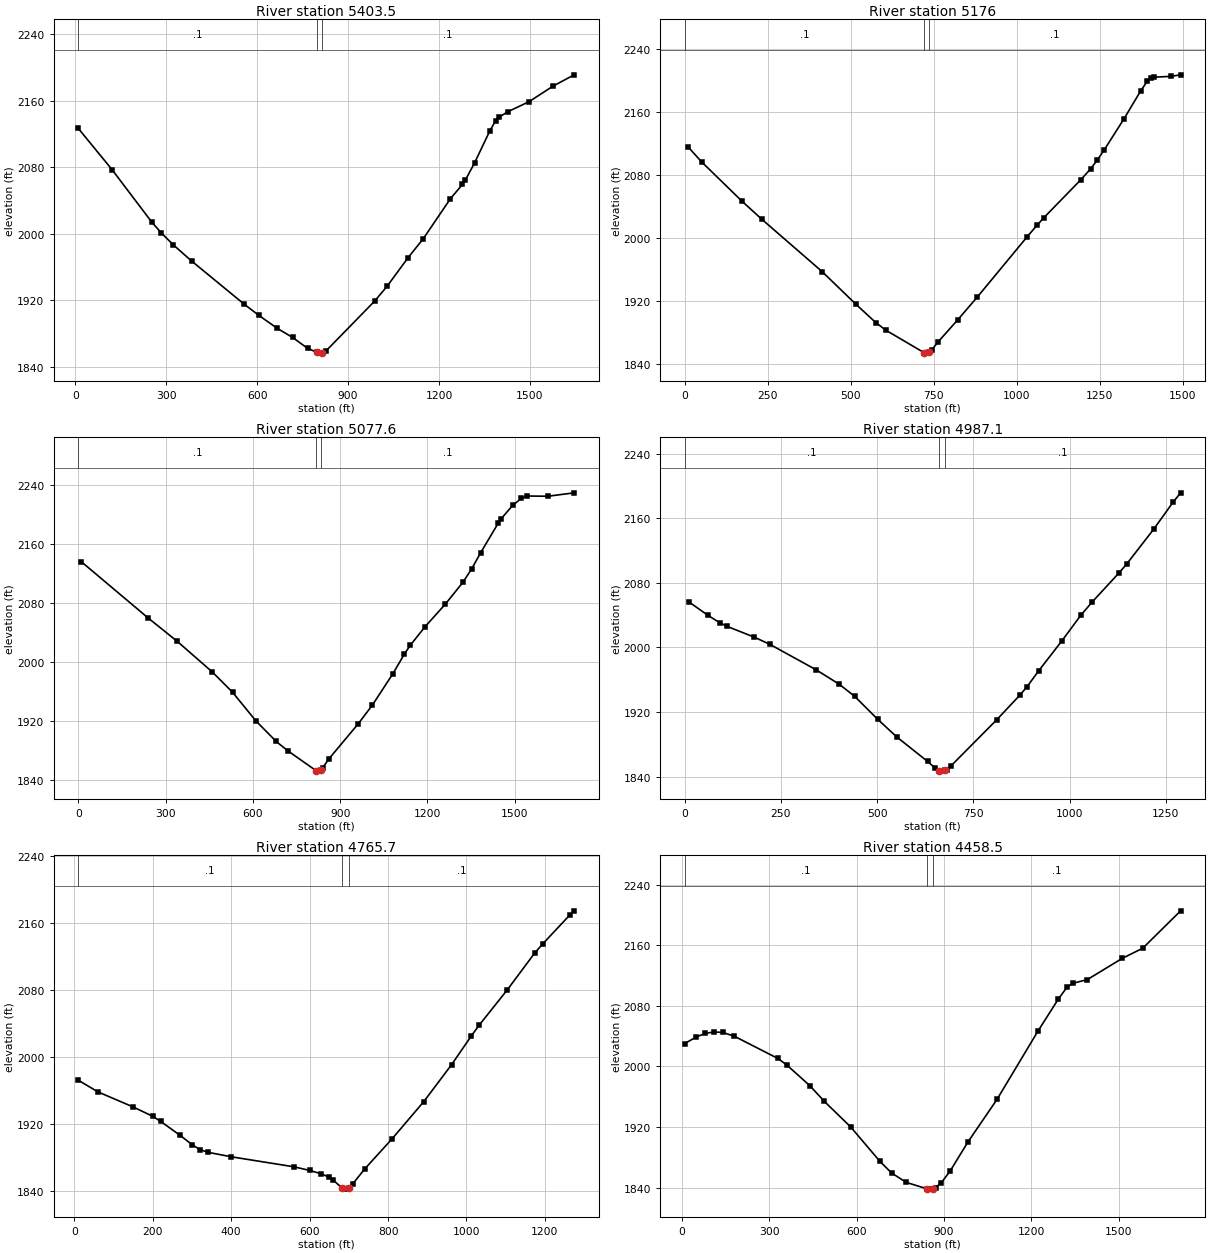
Type RM Length L Ch R = 1 ,5403.5  ,229.8,227.5,225.2
XS GIS Cut Line= 4
     1825252.454      106153.227     1825590.185      105566.801
     1825808.753      105266.237     1826131.245      104762.931
#Sta/Elev= 30
    10.1 2126.57   121.2 2077.18   252.5 2014.06   282.8 2001.53   323.2 1986.83
   383.8 1967.36   555.5 1916.02     606 1901.97   666.6 1886.44   716.9 1875.58
   767.1  1862.3   797.3 1857.73   807.3  1856.7     814 1856.87   827.4 1859.39
   988.1 1919.32  1028.3 1936.76  1098.2 1971.39    1148 1994.02  1237.6 2042.08
  1277.5 2059.37  1287.5 2064.86  1317.4 2085.13  1367.2 2123.22  1387.1 2136.05
  1397.1 2139.81  1426.9 2146.62  1496.7 2158.62  1576.4 2177.43  1646.1    2191
#Mann= 3 , 0 , 0
    10.1      .1       0   797.3    .045       0     814      .1       0
Bank Sta=797.3,814
XS Rating Curve= 0 ,0
Exp/Cntr=0.3,0.1

Type RM Length L Ch R = 1 ,5176    ,96.3,98.5,100.6
XS GIS Cut Line= 4
     1825462.691      106195.771     1825806.925      105673.046
     1825930.169      105460.556     1826151.159      104878.334
#Sta/Elev= 30
    10.1    2116    50.5 2097.09   171.6 2047.37   232.2 2024.05   413.9 1957.53
   514.8 1916.35   575.4 1892.83   605.7 1883.11   721.5 1854.38   724.1  1853.9
     734 1854.05   736.5 1854.99   743.8 1857.71   763.5 1868.25   822.4 1896.16
   881.6 1925.21  1032.2 2002.05  1062.4 2016.87  1082.5 2026.24    1193 2074.07
  1223.1 2088.24  1243.2 2099.35  1263.3 2111.76  1323.5 2151.69  1373.8 2187.17
  1393.8 2199.46  1403.9 2203.37  1413.9 2204.71  1464.2 2205.71  1494.3  2207.7
#Mann= 3 , 0 , 0
       0      .1       0   721.5    .045       0   736.5      .1       0
Bank Sta=721.5,736.5
XS Rating Curve= 0 ,0
Exp/Cntr=0.3,0.1

Type RM Length L Ch R = 1 ,5077.6  ,92.2,90.5,88.8
XS GIS Cut Line= 4
     1825578.574      106380.056     1825836.674      105783.541
     1826040.664      105498.804     1826229.689      104820.784
#Sta/Elev= 30
      10 2135.98     240 2059.58     340 2027.88     460 1986.51     530 1958.89
     610 1920.17     680 1892.17     720 1879.46   818.1 1852.26   820.1 1851.91
   833.1 1853.86   840.1 1856.52   860.1 1868.04   960.2 1915.25  1010.3 1941.29
  1080.7 1983.75  1120.9 2010.88    1141 2022.62  1191.3 2047.57  1261.7 2078.54
    1322 2108.11  1352.2 2126.41  1382.3 2147.84  1442.7 2187.88  1452.7 2193.95
  1492.9 2212.33  1523.1 2221.96  1543.2 2225.01  1613.6 2224.67  1704.1 2229.32
#Mann= 3 , 0 , 0
       0      .1       0   818.1    .045       0   833.1      .1       0
Bank Sta=818.1,833.1
XS Rating Curve= 0 ,0
Exp/Cntr=0.3,0.1

Type RM Length L Ch R = 1 ,4987.1  ,235.3,221.4,207.5
XS GIS Cut Line= 4
     1825772.927      106323.265     1825930.169      105826.039
     1826049.164      105630.548     1826244.654      105129.072
#Sta/Elev= 30
      10 2056.61    60.2 2039.68    90.3 2030.73   110.3 2025.96   180.5 2012.67
   220.6 2003.89     341 1972.31   401.2 1954.38   441.3 1939.41   501.4 1910.84
   551.3 1888.85     631 1858.68   650.9 1850.38   661.7 1847.29   670.8 1846.66
   676.7  1847.6   680.7 1848.23   690.7 1852.61   810.2 1910.07     870 1940.42
   889.9 1951.52   919.8 1971.04   979.6 2007.83  1029.4 2039.93  1059.3 2056.55
  1129.1 2092.61    1149 2103.66  1218.8 2146.59  1268.7 2179.74  1288.6 2191.53
#Mann= 3 , 0 , 0
       0      .1       0   661.7    .045       0   676.7      .1       0
Bank Sta=661.7,676.7
XS Rating Curve= 0 ,0
Exp/Cntr=0.3,0.1

Type RM Length L Ch R = 1 ,4765.7  ,308.3,307.2,306.1
XS GIS Cut Line= 4
     1826002.416      106353.014     1826223.405      105838.788
     1826206.406      105558.302     1826312.651      105137.572
#Sta/Elev= 30
      10 1972.18      60 1958.27   149.9 1940.25   199.9 1929.06   219.9 1923.05
   269.9 1906.24   299.8 1895.41   319.8 1889.45   339.8  1886.2   399.8 1880.78
   559.7 1868.81   599.8  1864.5     630  1860.4     650  1856.3   660.1 1852.84
   681.7  1843.9   690.2 1842.14   700.2 1843.53   710.2 1848.57   740.3 1866.17
   810.6 1902.44   891.2 1946.75   961.8 1990.66  1012.3 2025.08  1032.4 2038.01
  1103.1 2079.56  1173.7 2123.92  1193.9 2134.74  1264.5    2170  1274.6  2174.5
#Mann= 3 , 0 , 0
      10      .1       0   681.7    .045       0   700.2      .1       0
Bank Sta=681.7,700.2
XS Rating Curve= 0 ,0
Exp/Cntr=0.3,0.1

Type RM Length L Ch R = 1 ,4458.5  ,342.2,336.1,330
XS GIS Cut Line= 4
     1826497.219      106522.934     1826529.391      105864.287
     1826495.392      105503.054     1826339.185      104830.397
#Sta/Elev= 30
      10  2030.2      50 2038.93    79.9 2043.56   109.9 2045.38   139.9 2044.87
   179.8 2039.88   329.7 2010.43   359.7 2002.01   439.6 1974.45   489.6 1953.62
   579.5 1920.06   679.6 1874.76   719.9 1859.26   770.3 1846.81   840.8 1838.36
   850.9 1837.86     861 1838.21   871.1 1839.82   891.2 1846.53   921.5 1861.88
   981.9 1899.87  1082.3 1956.43  1222.4 2046.33  1292.5 2088.71  1322.5 2104.54
  1342.5  2109.7  1392.6 2114.69  1512.7 2142.74  1582.7 2156.07  1712.8 2205.46
#Mann= 3 , 0 , 0
      10      .1       0   840.8    .045       0     861      .1       0
Bank Sta=840.8,861
XS Rating Curve= 0 ,0
Exp/Cntr=0.3,0.1

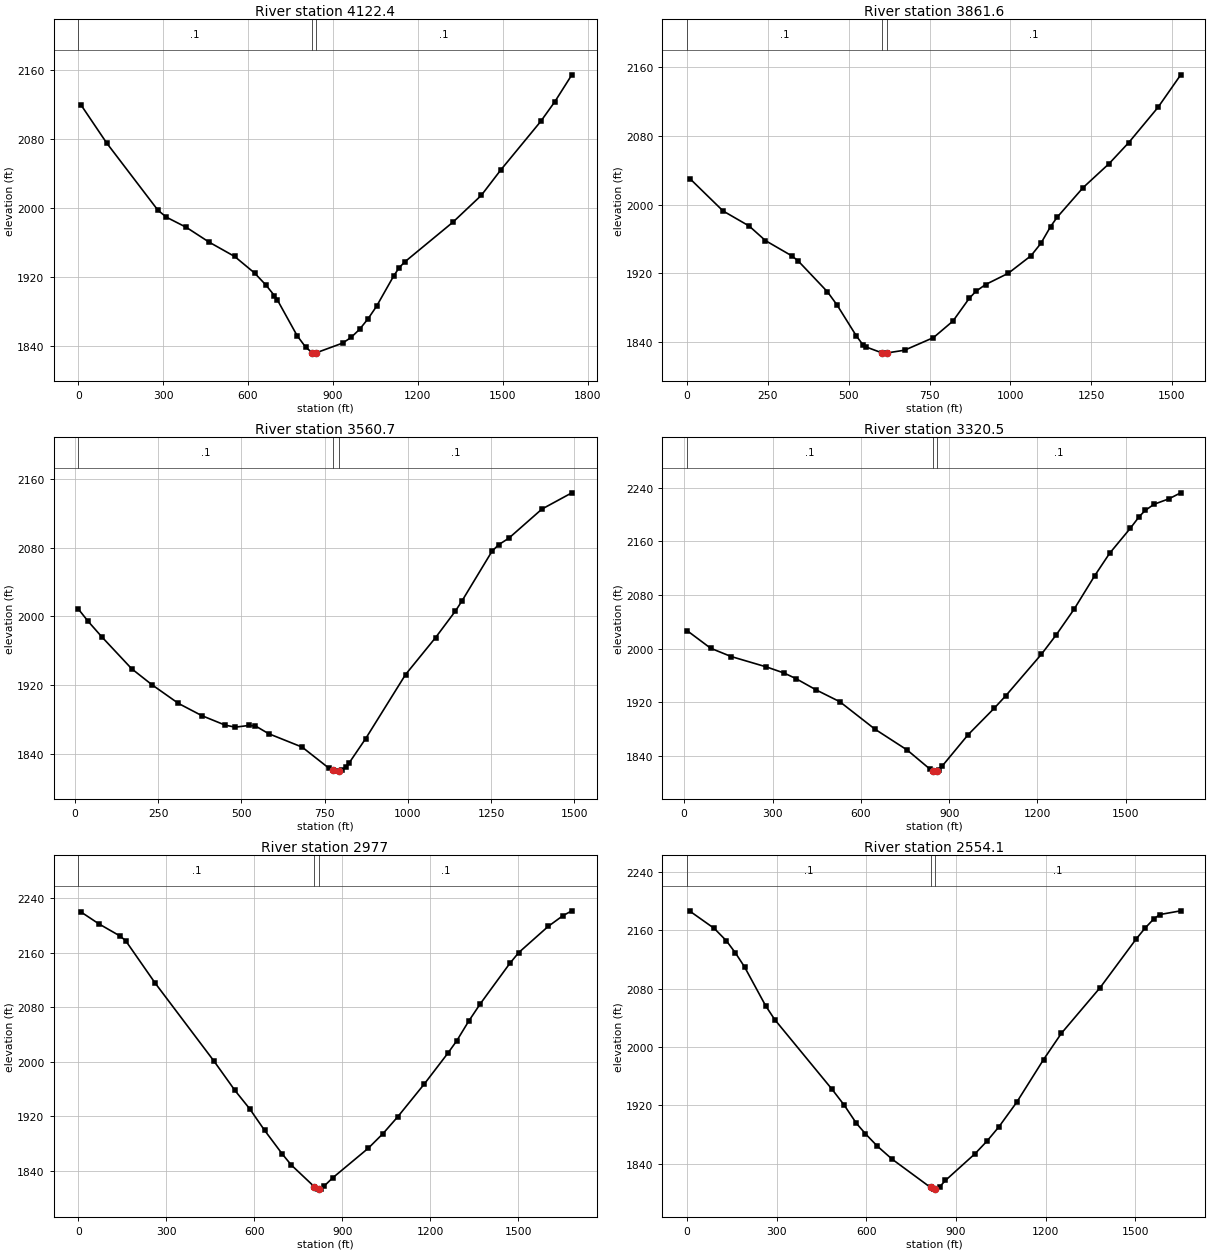
Type RM Length L Ch R = 1 ,4122.4  ,259.4,260.7,262
XS GIS Cut Line= 4
     1826853.066      106461.158     1826877.874      105758.042
     1826788.628      105545.552     1826448.305      104810.361
#Sta/Elev= 30
    10.1  2119.8   100.5  2075.7   281.4 1997.62   311.6 1989.43   381.9 1977.66
   462.3 1960.48   552.8 1943.76   623.1 1924.55   663.4 1910.52   693.5 1898.17
   703.6 1893.29   773.7 1851.61   803.8 1838.29   826.7 1831.92   833.8 1831.41
   841.7 1831.89     934 1843.04     964 1849.59     994 1859.01    1024 1871.28
    1054 1885.79  1114.1 1920.78  1134.1 1930.75  1154.1 1937.52  1324.1 1983.65
  1424.1 2014.75  1494.1 2044.76  1634.1 2100.71  1684.2 2123.72  1744.2 2154.93
#Mann= 3 , 0 , 0
       0      .1       0   826.7    .045       0   841.7      .1       0
Bank Sta=826.7,841.7
XS Rating Curve= 0 ,0
Exp/Cntr=0.3,0.1

Type RM Length L Ch R = 1 ,3861.6  ,306.5,301,295.3
XS GIS Cut Line= 4
      1827387.85       106013.03     1827103.113      105698.545
     1826979.869       105384.06     1826540.159      104757.983
#Sta/Elev= 30
    10.1 2029.64   111.1 1992.54   191.9 1974.96   242.4 1957.96   323.2 1940.35
   343.4 1934.35   434.2 1898.28     464 1882.85   523.6 1846.84   543.4 1836.83
   553.4 1834.04   602.6 1827.18     613 1826.84   617.6 1827.01   672.6 1830.24
     762  1844.9   822.4  1864.2   872.7 1890.65   892.9  1898.7   923.1 1906.73
   993.5 1919.88    1064  1940.4  1094.2 1954.65  1124.4  1974.3  1144.5 1985.09
  1225.1 2019.75  1305.6 2047.74    1366 2072.09  1456.6 2113.18  1527.1 2151.18
#Mann= 3 , 0 , 0
       0      .1       0   602.6    .045       0   617.6      .1       0
Bank Sta=602.6,617.6
XS Rating Curve= 0 ,0
Exp/Cntr=0.3,0.1

Type RM Length L Ch R = 1 ,3560.7  ,234.7,240.2,245.7
XS GIS Cut Line= 4
     1827532.343      105949.283     1827243.357       105375.56
     1827103.113       105167.32     1826707.882      104716.842
#Sta/Elev= 30
      10 2008.54    40.1 1993.91    80.3 1976.24   170.6 1938.81   230.9 1920.38
   311.2 1898.42   381.4 1884.19   451.7 1873.11   481.8 1870.81   521.9 1872.74
     542 1872.27   582.2 1863.16   682.6 1847.57   762.9 1823.06   774.7 1820.35
     783 1819.58     793 1819.86   803.1 1821.21   813.1 1823.99   823.2 1828.78
   873.4 1857.44   993.3 1932.12  1083.2 1975.02  1143.2 2006.16  1163.1 2018.07
    1253 2075.75    1273 2083.38    1303 2090.78  1402.8 2124.83  1492.7 2143.77
#Mann= 3 , 0 , 0
      10      .1       0   774.7    .045       0     793      .1       0
Bank Sta=774.7,793
XS Rating Curve= 0 ,0
Exp/Cntr=0.3,0.1

Type RM Length L Ch R = 1 ,3320.5  ,352.6,343.5,334.3
XS GIS Cut Line= 4
     1827783.447      105921.905     1827438.847      105303.314
     1827307.104      104942.081     1826926.233      104486.308
#Sta/Elev= 30
      10 2026.88    89.8 2000.72   159.6 1988.32   279.3 1972.86   339.1 1963.79
     379 1955.59   448.8 1938.47   528.6 1921.02   648.3 1880.02   757.4 1849.06
   836.3 1820.08  843.73 1818.25     856 1817.61  859.02  1818.3   865.8 1819.85
   875.7  1824.8   964.4 1871.86  1053.2 1911.34  1092.6 1930.04  1213.4 1991.73
  1263.7 2020.65  1324.2  2058.7  1394.6 2108.87    1445 2142.11  1515.4 2179.43
  1545.6 2196.81  1565.8 2205.94    1596 2215.18  1646.3 2223.26  1686.6 2232.22
#Mann= 3 , 0 , 0
      10      .1       0  843.73    .045       0  859.02      .1       0
Bank Sta=843.73,859.02
XS Rating Curve= 0 ,0
Exp/Cntr=0.3,0.1

Type RM Length L Ch R = 1 ,2977    ,428.8,422.9,417
XS GIS Cut Line= 4
     1828294.677      105506.722     1827802.397       105121.86
     1827498.345      104797.588     1827017.923      104416.617
#Sta/Elev= 30
    10.1 2219.97    70.5 2202.67   141.1  2185.2   161.3 2178.18     262 2115.77
   463.6 2000.49   534.2 1957.88   584.6  1930.8     635 1899.38   695.6 1864.41
   725.9 1848.43   804.8 1816.34   816.8 1812.83   819.8 1812.95   826.9 1813.22
     837  1816.8   867.3 1829.37   988.6 1872.92  1039.1 1894.55  1089.5 1919.36
    1180 1967.56  1260.4 2012.87  1290.5 2031.04  1330.7 2059.53  1370.9 2085.47
  1471.4 2144.77  1501.6 2160.54  1602.1 2199.04  1652.4  2214.8  1682.5 2221.86
#Mann= 3 , 0 , 0
       0      .1       0   804.8    .045       0   819.8      .1       0
Bank Sta=804.8,819.8
XS Rating Curve= 0 ,0
Exp/Cntr=0.3,0.1

Type RM Length L Ch R = 1 ,2554.1  ,378.1,365.9,353.7
XS GIS Cut Line= 4
     1828540.817      105070.807     1828042.319      104725.341
     1827655.587      104483.103     1827119.218      104239.899
#Sta/Elev= 30
    10.1 2185.65      91 2162.21   131.4 2145.33   161.7 2128.69   192.1 2109.61
   262.8 2056.29   293.1 2037.44   485.2 1941.83   525.6 1920.29   566.1 1895.56
   596.4 1881.12   636.3 1864.15   685.9 1846.25   814.5 1807.53   824.8  1805.2
   829.5 1805.27   844.6 1808.12   864.4 1817.12   963.6 1853.76  1003.3 1870.93
    1043 1890.35  1102.8 1924.13  1192.6 1982.59  1252.5 2018.68  1382.3  2081.3
    1502 2147.44    1532 2162.51  1561.9 2175.42  1581.9  2181.3  1651.8 2186.39
#Mann= 3 , 0 , 0
       0      .1       0   814.5    .045       0   829.5      .1       0
Bank Sta=814.5,829.5
XS Rating Curve= 0 ,0
Exp/Cntr=0.3,0.1

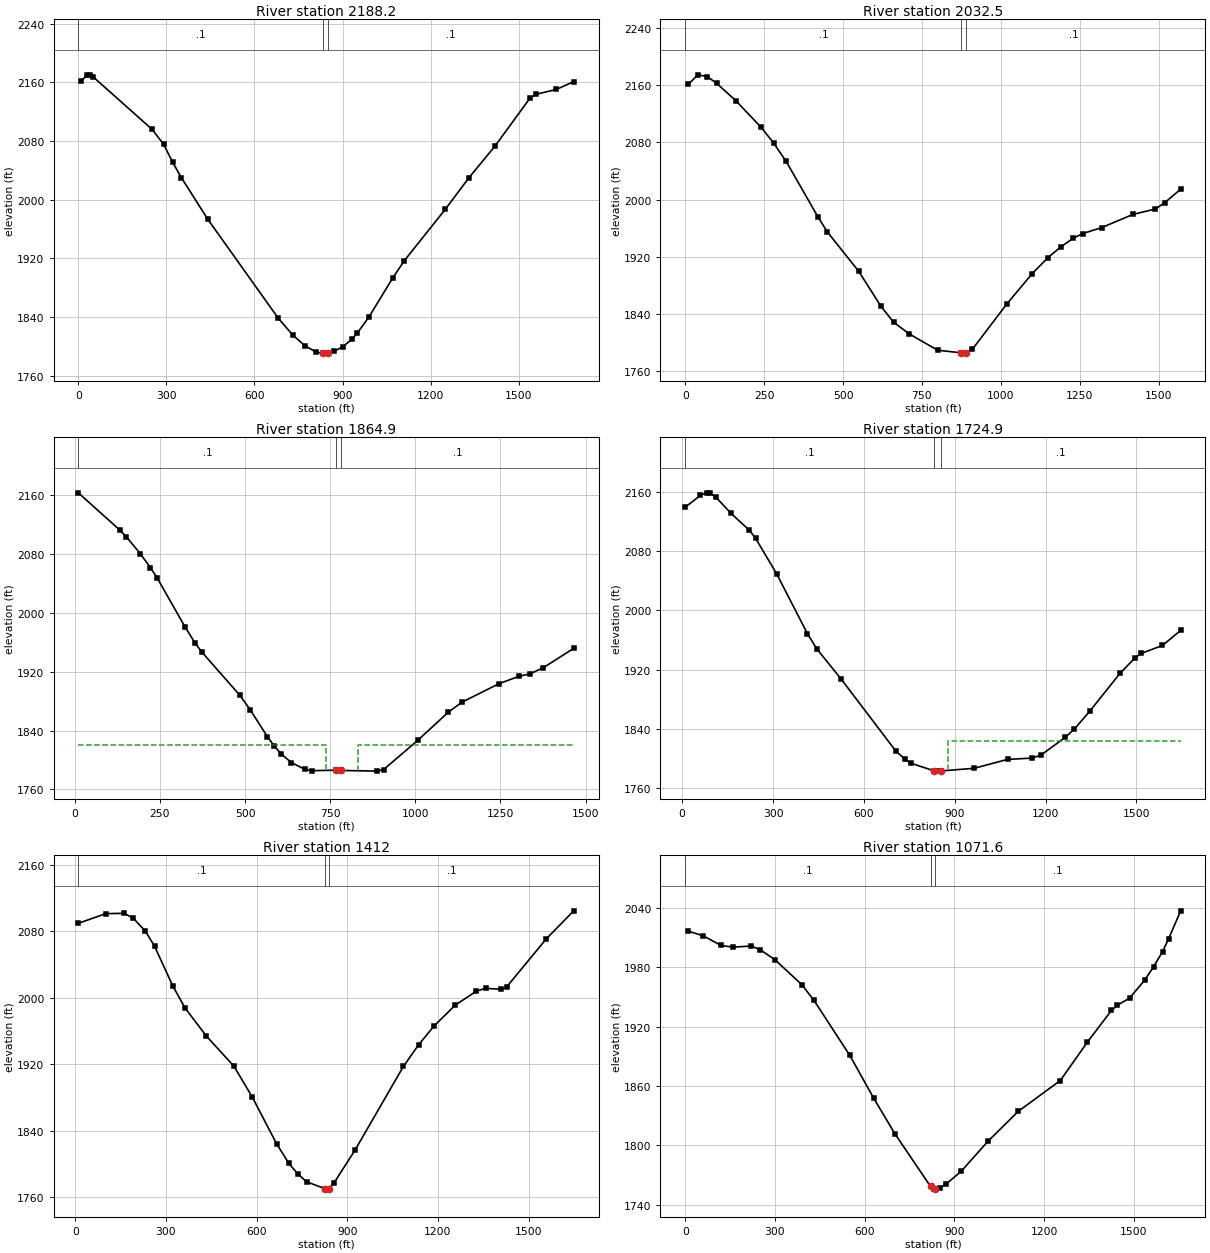
Type RM Length L Ch R = 1 ,2188.2  ,154.2,155.7,157.3
XS GIS Cut Line= 4
     1828815.505      104452.183     1828293.057      104308.861
     1827715.084      104279.112     1827166.191      104137.213
#Sta/Elev= 30
      10 2162.32    30.1 2169.75    40.1  2170.4    50.2  2167.7   250.8 2096.12
   290.9 2075.45     321 2051.29   351.1 2029.97   441.4 1973.04   681.4 1837.97
   731.3 1814.94   771.2 1800.84   811.2 1791.63   834.8 1790.73   841.1 1790.56
   849.8 1790.66     871 1793.03     901 1799.27   930.9 1809.25   950.9 1818.23
   990.8 1840.44  1070.6 1892.97  1110.5  1916.8  1249.8 1986.78  1329.4 2029.37
  1418.9 2072.97  1538.2 2138.49  1558.1 2143.76  1627.7 2150.39  1687.4 2161.15
#Mann= 3 , 0 , 0
       0      .1       0   834.8    .045       0   849.8      .1       0
Bank Sta=834.8,849.8
XS Rating Curve= 0 ,0
Exp/Cntr=0.3,0.1

Type RM Length L Ch R = 1 ,2032.5  ,157.5,167.6,177.7
XS GIS Cut Line= 4
     1828824.282      104389.607     1828203.811      104164.368
     1827846.828       104121.87     1827370.851      103845.633
#Sta/Elev= 30
      10 2161.22      40 2174.33      70 2171.93     100 2162.23     160 2138.38
     240 2101.21     280 2079.17     320 2053.27   420.1 1976.22   450.1 1955.01
   550.1 1899.64   620.1 1851.03   660.1 1828.79     710 1812.32   799.9 1789.63
   875.3 1785.95   889.8 1785.55   890.3 1785.61   909.7 1790.78  1019.6 1854.54
  1099.6 1896.62  1149.7 1919.07  1189.7 1933.77  1229.7 1946.17  1259.7  1952.6
  1319.8 1960.93  1419.8 1979.51  1489.9 1986.88  1519.9 1995.85  1569.9  2014.5
#Mann= 3 , 0 , 0
       0      .1       0   875.3    .045       0   890.3      .1       0
Bank Sta=875.3,890.3
XS Rating Curve= 0 ,0
Exp/Cntr=0.3,0.1

Type RM Length L Ch R = 1 ,1864.9  ,136.1,139.9,143.8
XS GIS Cut Line= 4
     1828764.785       104330.11      1828233.56      104109.121
     1827868.077      103879.631     1827464.346      103662.892
#Sta/Elev= 30
    10.1 2163.58   131.2 2113.27   151.4 2103.66   191.8 2081.01   222.1 2061.68
   242.3 2047.25     323 1981.63   353.3 1958.88   373.5 1946.65   484.5 1888.15
   514.8 1868.57   565.3 1831.93   585.4 1819.26   605.5 1808.56   635.6 1796.68
   675.7 1787.33   695.8 1785.59   767.9 1786.22  776.57 1784.96   782.9 1785.87
   886.5 1784.96   906.6 1787.04  1006.9  1826.8  1096.6 1865.08  1136.4 1878.65
    1246 1904.02  1305.8 1914.18  1335.6 1917.12  1375.5 1925.59  1465.1 1952.03
#Mann= 3 , 0 , 0
    10.1      .1       0   767.9    .045       0   782.9      .1       0
#XS Ineff= 2 , 0
          738.63 1820.88   830.8         1820.88
Permanent Ineff=
       F       F
Bank Sta=767.9,782.9
XS Rating Curve= 0 ,0
Exp/Cntr=0.3,0.1

Type RM Length L Ch R = 1 ,1724.9  ,309.9,313,316
XS GIS Cut Line= 4
     1828853.872       104349.84     1828344.054      104062.373
     1827982.822      103747.888     1827531.812      103380.722
#Sta/Elev= 30
    10.1 2139.35    60.5 2155.39    80.7 2158.76    90.8 2158.47     111 2153.03
   161.5 2130.91     222 2108.19   242.2  2097.5   312.8 2048.75   413.7  1968.4
     444 1948.25   524.7 1907.32     705 1810.21   734.9 1799.08   754.9 1793.61
   831.8 1783.21   844.7 1782.87   854.7 1783.13   964.4  1786.7  1074.3 1798.75
  1154.5 1800.44  1184.5 1804.48  1264.8 1828.53  1294.8 1839.64    1345 1863.46
  1445.3 1914.77  1495.4 1935.95  1515.4 1941.81  1585.6 1952.58  1645.8 1972.87
#Mann= 3 , 0 , 0
    10.1      .1       0   831.8    .045       0   854.7      .1       0
#XS Ineff= 2 , 0
                          876.12         1824.05
Permanent Ineff=
       F       F
Bank Sta=831.8,854.7
XS Rating Curve= 0 ,0
Exp/Cntr=0.3,0.1

Type RM Length L Ch R = 1 ,1412    ,335.1,340.3,345.5
XS GIS Cut Line= 4
     1828928.787      104255.375     1828475.798      103794.635
      1828225.06      103509.899     1827707.052      103162.081
#Sta/Elev= 30
    10.1 2089.53     101 2101.23   161.5 2101.54   191.8 2095.82   232.2 2080.05
   262.5 2061.93   323.1 2013.95   363.4 1987.68   434.1  1953.8     525 1917.68
   585.6 1880.63   666.1 1824.43     706 1801.19     736 1788.14   765.9 1778.58
   825.8 1770.39   835.8 1769.78  838.96 1770.42   855.8 1776.97   925.7 1816.68
  1085.9  1917.4  1136.2 1943.42  1186.5  1965.7    1257 1991.03  1327.4 2007.96
  1357.6 2011.34  1407.9 2010.25  1428.1  2013.3  1558.9 2070.95  1649.5 2104.58
#Mann= 3 , 0 , 0
    10.1      .1       0   825.8    .045       0  838.96      .1       0
Bank Sta=825.8,838.96
XS Rating Curve= 0 ,0
Exp/Cntr=0.3,0.1

Type RM Length L Ch R = 1 ,1071.6  ,427.6,432.7,437.7
XS GIS Cut Line= 4
      1829026.87      104189.816     1828718.037      103628.893
     1828556.544      103327.158     1828398.129      102672.433
#Sta/Elev= 30
      10 2016.62      60 2011.92   120.1 2002.15   160.1 2000.43   220.1 2001.58
   250.1 1997.95   300.2 1987.69   390.2 1962.33   430.2 1946.69   550.3  1890.9
   630.3  1847.5   700.7 1811.77     820  1758.4   831.6 1755.63     835 1755.67
   851.7 1756.99   871.8 1760.66   922.2 1773.54  1012.7 1804.27  1113.3 1834.31
    1254 1865.52  1344.5 1904.37  1424.9 1936.42    1445 1941.77  1485.3 1948.85
  1535.5 1966.87  1565.7 1980.55  1595.8 1996.01    1616  2008.9  1656.2 2037.19
#Mann= 3 , 0 , 0
       0      .1       0     820    .045       0     835      .1       0
Bank Sta=820,835
XS Rating Curve= 0 ,0
Exp/Cntr=0.3,0.1

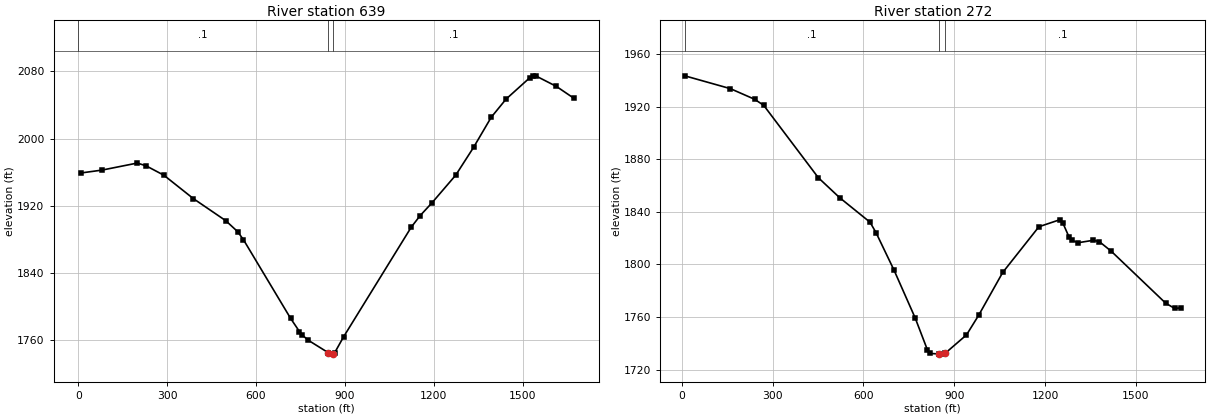
Type RM Length L Ch R = 1 ,639     ,359.6,366.9,374.2
XS GIS Cut Line= 4
      1829140.09      104155.553     1829096.269      103539.648
     1828973.025      103089.169     1828976.795      102499.342
#Sta/Elev= 30
      10 1959.16    79.7 1962.51   199.2 1970.91   229.1 1967.55   288.8 1956.45
   388.4  1928.6     498 1902.29   537.8 1889.35   557.7 1879.62   716.8  1786.1
   746.6 1770.48   756.6 1766.12   776.5 1760.06   843.4 1745.41   855.9 1743.56
   858.4 1744.02   865.9 1745.42   895.7 1764.14  1124.5 1894.79  1154.5 1908.46
  1194.5 1923.71  1274.4 1956.52  1334.4 1989.44  1394.4 2025.47  1444.4 2047.01
  1524.4 2072.39  1534.4 2074.47  1544.4 2074.69  1614.4 2062.08  1674.3 2047.77
#Mann= 3 , 0 , 0
       0      .1       0   843.4    .045       0   858.4      .1       0
Bank Sta=843.4,858.4
XS Rating Curve= 0 ,0
Exp/Cntr=0.3,0.1

Type RM Length L Ch R = 1 ,272     ,273.3,272,270.8
XS GIS Cut Line= 4
     1829194.014      104147.369     1829368.256      103560.897
     1829406.504      103174.165     1829623.047       102563.84
#Sta/Elev= 30
      10 1943.66   160.5  1933.9   240.7  1925.8   270.8 1921.16   451.3 1866.03
   521.5 1850.88   621.8 1832.22   641.7 1824.26   701.5 1795.53   771.2  1759.2
   811.1 1735.19   821.1  1732.2     851 1731.87   860.9 1731.72   870.9 1732.51
   940.6 1746.36   980.5 1761.19  1060.2  1793.9  1179.8 1828.73  1249.5 1834.12
  1259.5 1831.27  1279.4  1820.9  1289.4 1818.29  1309.3 1816.56  1359.1  1818.4
    1379 1817.48  1418.9 1810.07  1598.2 1770.61  1628.1 1766.54    1648 1766.91
#Mann= 3 , 0 , 0
      10      .1       0     851    .045       0   870.9      .1       0
Bank Sta=851,870.9
XS Rating Curve= 0 ,0
Exp/Cntr=0.3,0.1

Chan Stop Cuts=-1
Use User Specified Reach Order=0